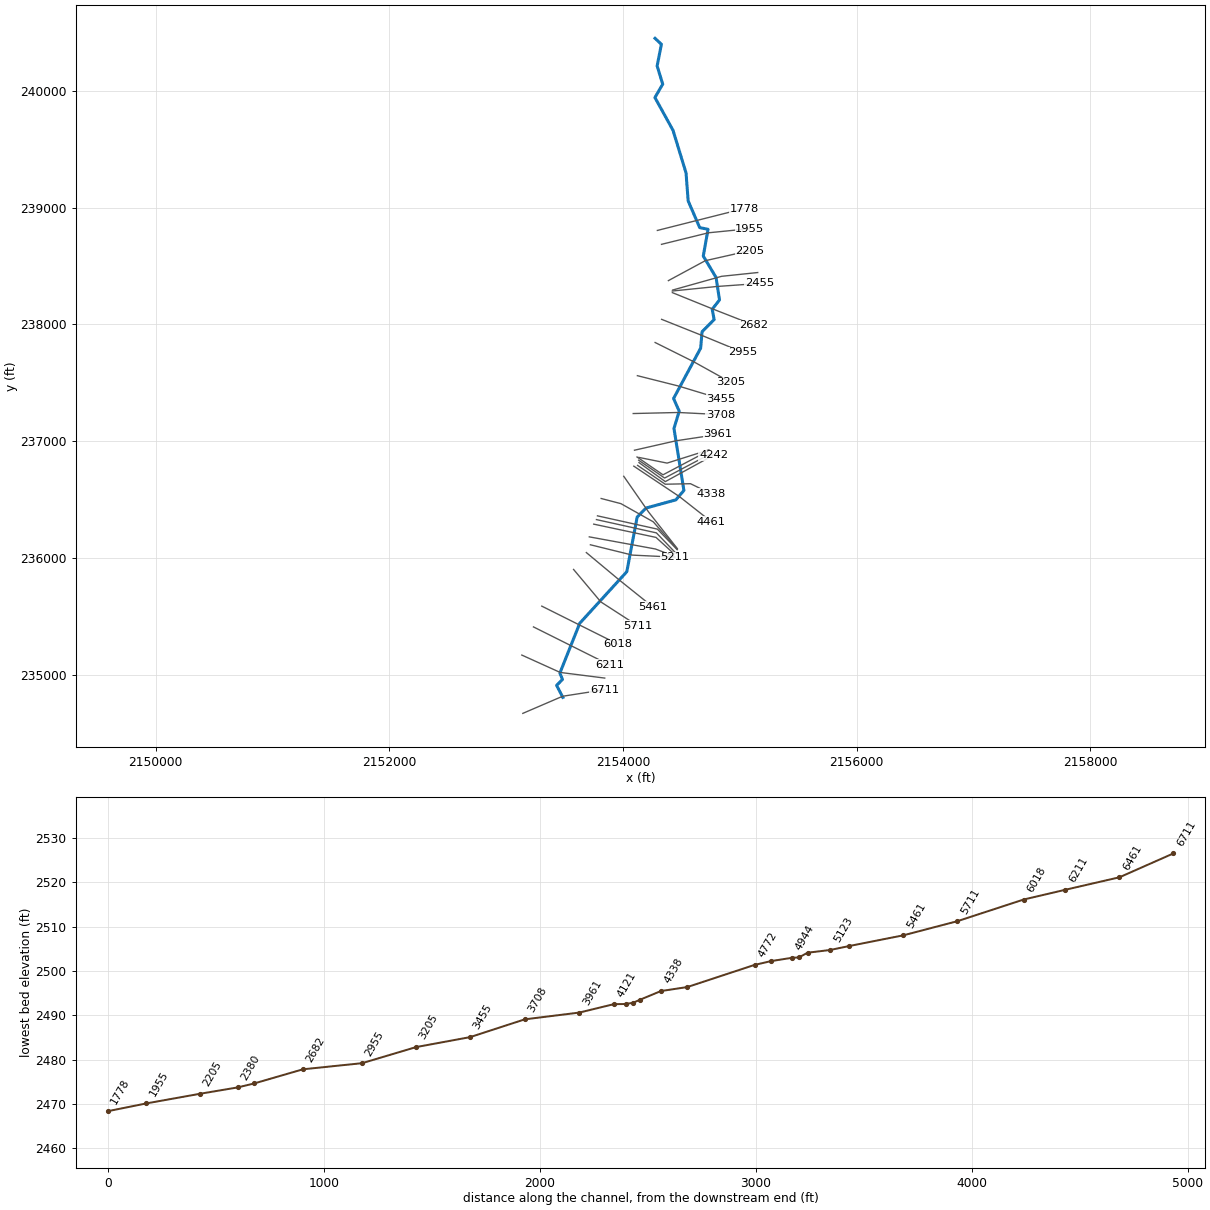
--- LLAURELCK.prj (project) ---

Proj Title=LLAURELCK
Current Plan=p01
Default Exp/Contr=0,0
English Units
Geom File=g01
Flow File=f01
Plan File=p01
Background Map Layer=Inundation Boundary (01pct Value_0)
BEGIN DESCRIPTION:
Stream Name: Little Laurel Creek
Flood Zone: Approximate
Monroe County, West Virginia
HEC-RAS Version: 5.0.7
Vertical Datum: NAVD88
Projection: NAD 1983 StatePlane West Virginia S FIPS 4702 (US Feet)
LiDAR: 2016, 1-meter
Land Use: 2016 NLCD
Hydrologic Method:
SIR2010-5033 regression equations
Model Notes:
Downstream boundary condition uses known water surface elevation from Laurel Creek (I)
END DESCRIPTION:
DSS File=dss
DSS Export Rating Curves= 0
DSS Export Rating Curve Sorted= 0
DSS Export Volume Flow Curves= 0
DXF OffsetX= 0
DXF OffsetY= 0
DXF ScaleX= 0
DXF ScaleY= 0

--- LLAURELCK.p01 (plan) ---

Plan Title=Floodplain
Program Version=5.07
Short Identifier=Floodplain
Geom File=g01
Flow File=f01
Subcritical Flow
K Sum by GR= 0
Std Step Tol= 0.01
Critical Tol= 0.01
Num of Std Step Trials= 20
Max Error Tol= 0.3
Flow Tol Ratio= 0.001
Split Flow NTrial= 30
Split Flow Tol= 0.02
Split Flow Ratio= 0.02
Log Output Level= 0
Friction Slope Method= 1
Unsteady Friction Slope Method= 2
Unsteady Bridges Friction Slope Method= 1
Parabolic Critical Depth
Global Vel Dist= 0 , 0 , 0
Global Log Level= 0
CheckData=False
Encroach Param=-1 ,0,0, 0
Computation Interval=0.1SEC
Output Interval=1MIN
Instantaneous Interval=Max Profile
Mapping Interval=1HOUR
Computation Time Step Use Courant=        0
Computation Time Step Use Time Series=    0
Computation Time Step Count To Double=0
Computation Time Step Max Doubling=0
Computation Time Step Max Halving=0
Computation Time Step Residence Courant=0
Run HTab= 0
Run UNet= 0
Run Sediment= 0
Run PostProcess= 0
Run WQNet= 0
Run RASMapper=-1
UNET Theta= 0
UNET Theta Warmup= 0
UNET ZTol= 0
UNET ZSATol= 0
UNET MxIter= 0
UNET Max Iter WO Improvement= 0
UNET MaxInSteps= 0
UNET DtIC= 0
UNET DtMin= 0
UNET MaxCRTS= 0
UNET WFStab= 0
UNET SFStab= 0
UNET WFX= 1
UNET SFX= 1
UNET 1D Methodology=Finite Difference
UNET DSS MLevel= 1
UNET Pardiso=0
UNET DZMax Abort= 0
UNET Use Existing IB Tables= 0
UNET Froude Reduction=False
UNET Froude Limit= 0
UNET Froude Power= 0
UNET D1 Cores= 0
UNET D2 Coriolis=0
UNET D2 Cores= 0
UNET D2 Theta= 1
UNET D2 Theta Warmup= 1
UNET D2 Z Tol= 0.01
UNET D2 Volume Tol= 0.01
UNET D2 Max Iterations= 20
UNET D2 Equation= 0
UNET D2 RampUpFraction=0.1
UNET D2 TimeSlices= 1
UNET D2 BCVolumeCheck=0
UNET D1D2 MaxIter= 0
UNET D1D2 ZTol=0.01
UNET D1D2 QTol=0.1
UNET D1D2 MinQTol=1
DSS File=dss
Write IC File= 0
Write IC File at Fixed DateTime=0
Write IC File at Sim End=0
Echo Input=False
Echo Parameters=False
Echo Output=False
Write Detailed= 0
HDF Write Warmup=0
HDF Write Time Slices=0
HDF Flush=0
HDF Face Node Velocities=0
HDF Compression= 1
HDF Chunk Size= 1
HDF Spatial Parts= 1
HDF Use Max Rows=0
HDF Fixed Rows= 1
Calibration Method= 0
Calibration Iterations= 20
Calibration Max Change=0.05
Calibration Tolerance=0.2
Calibration Maximum=1.5
Calibration Minimum=0.5
Calibration Optimization Method= 1
WQ AD Non Conservative
WQ ULTIMATE=-1
WQ Max Comp Step=1HOUR
WQ Output Interval=15MIN
WQ Output Selected Increments= 0
WQ Output face flow=0
WQ Output face velocity=0
WQ Output face area=0
WQ Output face dispersion=0
WQ Output cell volume=0
WQ Output cell surface area=0
WQ Output cell continuity=0
WQ Output cumulative cell continuity=0
WQ Output face conc=0
WQ Output face dconc_dx=0
WQ Output face courant=0
WQ Output face peclet=0
WQ Output face adv mass=0
WQ Output face disp mass=0
WQ Output cell mass=0
WQ Output cell source sink temp=0
WQ Output nsm pathways=0
WQ Output nsm derived pathways=0
WQ Output MaxMinRange=-1
WQ Daily Max Min Mean=-1
WQ Daily Range=0
WQ Daily Time=0
WQ Create Restart=0
WQ Fixed Restart=0
WQ System Summary=0
WQ Write To DSS=0
WQ Use Fixed Temperature=0
Sorting and Armoring Iterations= 10
XS Update Threshold= 0.02
Bed Roughness Predictor= 0
Hydraulics Update Threshold= 0.02
Energy Slope Method= 1
Volume Change Method= 1
Sediment Retention Method= 0
XS Weighting Method= 0
Number of US Weighted Cross Sections= 1
Number of DS Weighted Cross Sections= 1
Upstream XS Weight=0
Main XS Weight=1
Downstream XS Weight=0
Number of DS XS's Weighted with US Boundary= 1
Upstream Boundary Weight= 1
Weight of XSs Associated with US Boundary= 0
Number of US XS's Weighted with DS Boundary= 1
Downstream Boundary Weight= 0.5
Weight of XSs Associated with DS Boundary= 0.5
Percentile Method= 0
Sediment Output Level= 3
Mass or Volume Output= 0
Output Increment Type= 1
Profile and TS Output Increment= 1
XS Output Flag= 0
XS Output Increment= 10
Write Gradation File= 0
Read Gradation Hotstart= 0
Write HDF5 File= 1
Write Binary Output= 1
Write DSS Sediment File= 0
SV Curve= 0
Specific Gage Flag= 0

--- LLAURELCK.f01 (steady flow) ---

Flow Title=Flow
Program Version=5.07
Number of Profiles= 6
Profile Names=01pct,10pct,04pct,02pct,0_2pct,01plus
River Rch & RM=LLAURELCK,Main            ,6711
     547     289     384     463     765     810
River Rch & RM=LLAURELCK,Main            ,6018
     596     316     419     505     832     882
River Rch & RM=LLAURELCK,Main            ,3961
     662     352     467     561     922     979
River Rch & RM=LLAURELCK,Main            ,2455
     721     385     509     612    1000    1070
River Rch & RM=LLAURELCK,Main            ,24
    1430     785    1030    1220    1970    2120
Boundary for River Rch & Prof#=LLAURELCK,Main            , 1
Up Type= 0
Dn Type= 1
Dn Known WS=2457.894
Boundary for River Rch & Prof#=LLAURELCK,Main            , 2
Up Type= 0
Dn Type= 1
Dn Known WS=2456.784
Boundary for River Rch & Prof#=LLAURELCK,Main            , 3
Up Type= 0
Dn Type= 1
Dn Known WS=2457.113
Boundary for River Rch & Prof#=LLAURELCK,Main            , 4
Up Type= 0
Dn Type= 1
Dn Known WS=2457.493
Boundary for River Rch & Prof#=LLAURELCK,Main            , 5
Up Type= 0
Dn Type= 1
Dn Known WS=2458.867
Boundary for River Rch & Prof#=LLAURELCK,Main            , 6
Up Type= 0
Dn Type= 1
Dn Known WS=2458.988
DSS Import GetInterval= 0
DSS Import GetPeak= 0
DSS Import FillOption= 0

--- LLAURELCK.g01 (geometry) ---

Geom Title=Geometry
Program Version=5.07

River Reach=LLAURELCK       ,Main
Reach XY= 30
2153486.00900002234804.2120000032153432.62300001234907.077000011
2153482.97100001 234958.292000022153460.40099999235012.111000004
2153630.54000001235439.195000001     2154033.318 235881.03499997
2154121.85899999236348.917000011      2154197.38236426.173999993
     2154453.456236496.485999995     2154522.033236577.214999976
2154436.96300001237107.596999979     2154481.881237256.315000024
2154433.49100001237364.5419999852154665.26200001237795.965000008
     2154677.415237936.5900000052154780.71300002238040.756999993
      2154764.22238129.2990000172154826.72000002238209.160000008
     2154797.206238400.999999993     2154687.832238585.028000007
2154728.62999999238814.194000008     2154657.449238828.083000002
2154558.49099999239057.250000009     2154540.262239296.833000019
2154428.28300002239663.152999975     2154273.769239942.666999985
2154340.60899999240057.2500000282154292.86600002240213.500000004
2154329.44400001240398.8790000042154274.89837903 240449.82393981

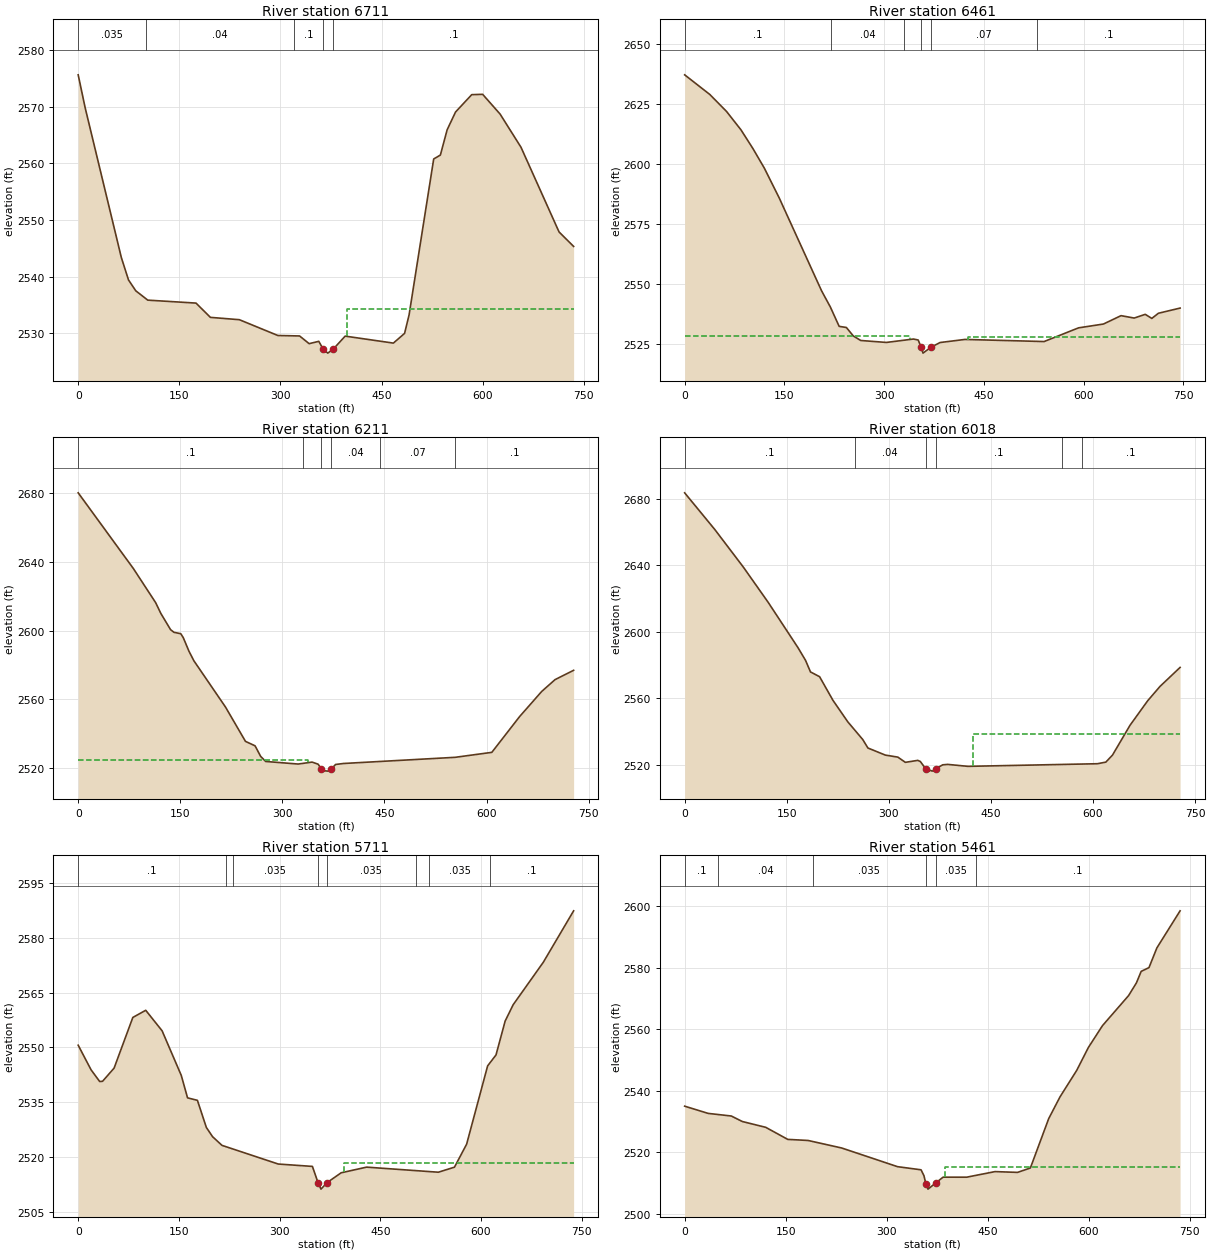
Type RM Length L Ch R = 1 ,6711    ,250,250,250
XS GIS Cut Line= 3
     2153143.271       234667.35     2153483.718      234813.946
      2153843.45      234870.029
#Sta/Elev= 30
       0 2575.62    10.3 2569.83    63.9 2543.42    74.6 2539.43    85.4 2537.51
   103.2 2535.86   174.7 2535.34   196.1 2532.82     239 2532.41   296.1 2529.62
   328.3 2529.54   342.5 2528.18   356.8 2528.59   363.22527.237   370.1 2526.51
   378.22527.213   395.9 2529.51   467.4 2528.28     484 2529.99   490.7 2533.26
   527.2 2560.77   537.1 2561.46   547.1 2565.91   559.6 2569.06   583.6 2572.12
   599.8 2572.18   625.7 2568.69   656.7 2562.83   713.1 2547.89   734.7 2545.34
#Mann= 5 ,-1 , 0
       0    .035       0     100     .04       0     320      .1       0
   363.2    .045       0   378.2      .1       0
#XS Ineff= 2 , 0
                          398.64         2534.21
Permanent Ineff=
       F       F
Bank Sta=363.2,378.2
XS Rating Curve= 0 ,0
Exp/Cntr=0.3,0.1

Type RM Length L Ch R = 1 ,6461    ,250.4,250,244.8
XS GIS Cut Line= 3
     2153134.705      235166.788     2153462.807      235018.127
     2153844.527      234969.676
#Sta/Elev= 30
       0  2637.2    37.8 2629.01      63 2621.92    84.7 2614.25   102.7 2606.43
     120 2598.19   142.3 2585.79   205.9 2547.11   219.2 2540.31   232.3 2532.29
   243.2 2531.81   253.6 2528.29   264.8 2526.39   303.4 2525.58     344    2527
   351.2 2526.59   355.42523.727   358.4 2521.12     3702523.502     384 2525.54
   421.4 2526.83   540.5 2525.95   592.3 2531.66   629.7 2533.25   656.2 2536.75
     676 2535.75   692.6  2537.3   702.5  2535.6   712.4 2537.75     745 2539.91
#Mann= 6 ,-1 , 0
       0      .1       0     220     .04       0     330     .07       0
   355.4    .045       0     370     .07       0  530.21      .1       0
#XS Ineff= 2 , 0
          339.09 2528.09  425.92         2527.81
Permanent Ineff=
       F       F
Bank Sta=355.4,370
XS Rating Curve= 0 ,0
Exp/Cntr=0.3,0.1

Type RM Length L Ch R = 1 ,6211    ,192.8,192.9,192.6
XS GIS Cut Line= 3
     2153234.457      235408.006     2153560.028       235245.22
       2153885.6      235082.434
#Sta/Elev= 30
       0 2680.12    81.1 2636.09   113.8 2616.29   121.4 2610.04   135.8 2600.54
   140.7 2599.03   150.8  2598.2   154.4 2595.93   162.7  2588.1     170 2582.48
   216.5 2555.55   245.8 2535.62   259.9 2533.03   268.1  2526.9   275.5 2523.93
   323.2 2522.43   343.7 2523.56   352.5 2522.36   357.42519.611   359.9 2518.58
   367.2 2518.31   371.92519.537   378.2 2522.18   390.1 2522.76     554 2526.34
   607.8 2529.23   648.7 2550.06   681.1 2564.64   700.7 2571.51     728 2576.93
#Mann= 6 ,-1 , 0
       0      .1       0     330     .04       0   357.4    .045       0
   371.9     .04       0     444     .07       0     554      .1       0
#XS Ineff= 2 , 0
          337.89 2524.55
Permanent Ineff=
       F       F
Bank Sta=357.4,371.9
XS Rating Curve= 0 ,0
Exp/Cntr=0.3,0.1

Type RM Length L Ch R = 1 ,6018    ,308.1,307.1,301.3
XS GIS Cut Line= 3
     2153305.637      235585.957     2153631.209      235423.171
      2153956.78      235260.386
#Sta/Elev= 30
       0 2683.48    44.2 2661.47    85.9    2639   122.5 2617.77   166.6 2590.33
   177.6 2582.75   184.9 2575.77   198.3 2572.89   217.8 2558.77   239.8 2545.72
   261.7 2535.11   269.3 2530.02   294.9 2525.75   313.2 2524.54   324.3  2521.4
   342.6 2522.58   346.3  2521.9   354.22517.535     364 2516.11   369.12517.556
   379.2  2519.9   386.6 2520.16   416.2 2518.98   606.6 2520.56   618.9 2521.53
   628.7 2525.77   654.4 2543.67   680.3 2558.39   698.4 2567.02     728 2578.49
#Mann= 6 ,-1 , 0
       0      .1       0     250     .04       0   354.2    .045       0
   369.1      .1       0     554    .035       0     584      .1       0
#XS Ineff= 2 , 0
                          424.41         2538.16
Permanent Ineff=
       F       F
Bank Sta=354.2,369.1
XS Rating Curve= 0 ,0
Exp/Cntr=0.3,0.1

Type RM Length L Ch R = 1 ,5711    ,247.8,250,248.2
XS GIS Cut Line= 3
      2153577.73      235900.314     2153810.964      235622.147
     2154125.757      235418.436
#Sta/Elev= 30
       0 2550.62    19.2 2543.88      32 2540.68    36.3 2540.74    53.5 2544.35
    81.4 2558.22   100.6 2560.18     125 2554.57   153.6 2542.33   162.9 2536.21
   177.6 2535.53   190.9 2528.11   200.2 2525.57   214.2  2523.2     298 2518.09
   348.9 2517.44   357.62512.822   361.7 2511.22   370.52512.967   391.7 2515.69
   429.6 2517.24   536.5 2515.85   560.5 2517.23   578.6 2523.52   609.9 2544.96
   622.4 2547.96     636 2557.23   647.9 2561.69   692.8 2573.32     738 2587.41
#Mann= 8 ,-1 , 0
       0      .1       0     220     .06       0     230    .035       0
   357.6    .045       0   370.5    .035       0  503.01      .1       0
  523.01    .035       0  613.01      .1       0
#XS Ineff= 2 , 0
                          395.68         2518.26
Permanent Ineff=
       F       F
Bank Sta=357.6,370.5
XS Rating Curve= 0 ,0
Exp/Cntr=0.3,0.1

Type RM Length L Ch R = 1 ,5461    ,244.3,250,256.3
XS GIS Cut Line= 3
     2153686.993      236044.838     2153965.596      235812.445
     2154256.441      235579.156
#Sta/Elev= 30
       0    2535    34.9 2532.65    69.3  2531.8    85.5 2530.02   120.4 2528.12
   153.1  2524.2   183.3 2523.85   233.2  2521.4   316.1 2515.33     351 2514.31
   355.3 2512.39   358.1 2509.82   361.3 2508.03   372.62509.997   383.7 2511.92
   418.7 2511.91   460.9 2513.73   494.2 2513.47   513.3  2514.9   540.5 2530.94
   557.3 2538.02   582.1 2546.63   599.4 2554.07   620.4 2561.19   659.1 2570.94
   670.8  2575.1   677.8 2578.82   689.4 2580.05   701.1 2586.44   735.6 2598.51
#Mann= 6 ,-1 , 0
       0      .1       0      50     .04       0     190    .035       0
   358.1    .045       0   372.6    .035       0   432.8      .1       0
#XS Ineff= 2 , 0
                          385.99         2515.25
Permanent Ineff=
       F       F
Bank Sta=358.1,372.6
XS Rating Curve= 0 ,0
Exp/Cntr=0.3,0.1

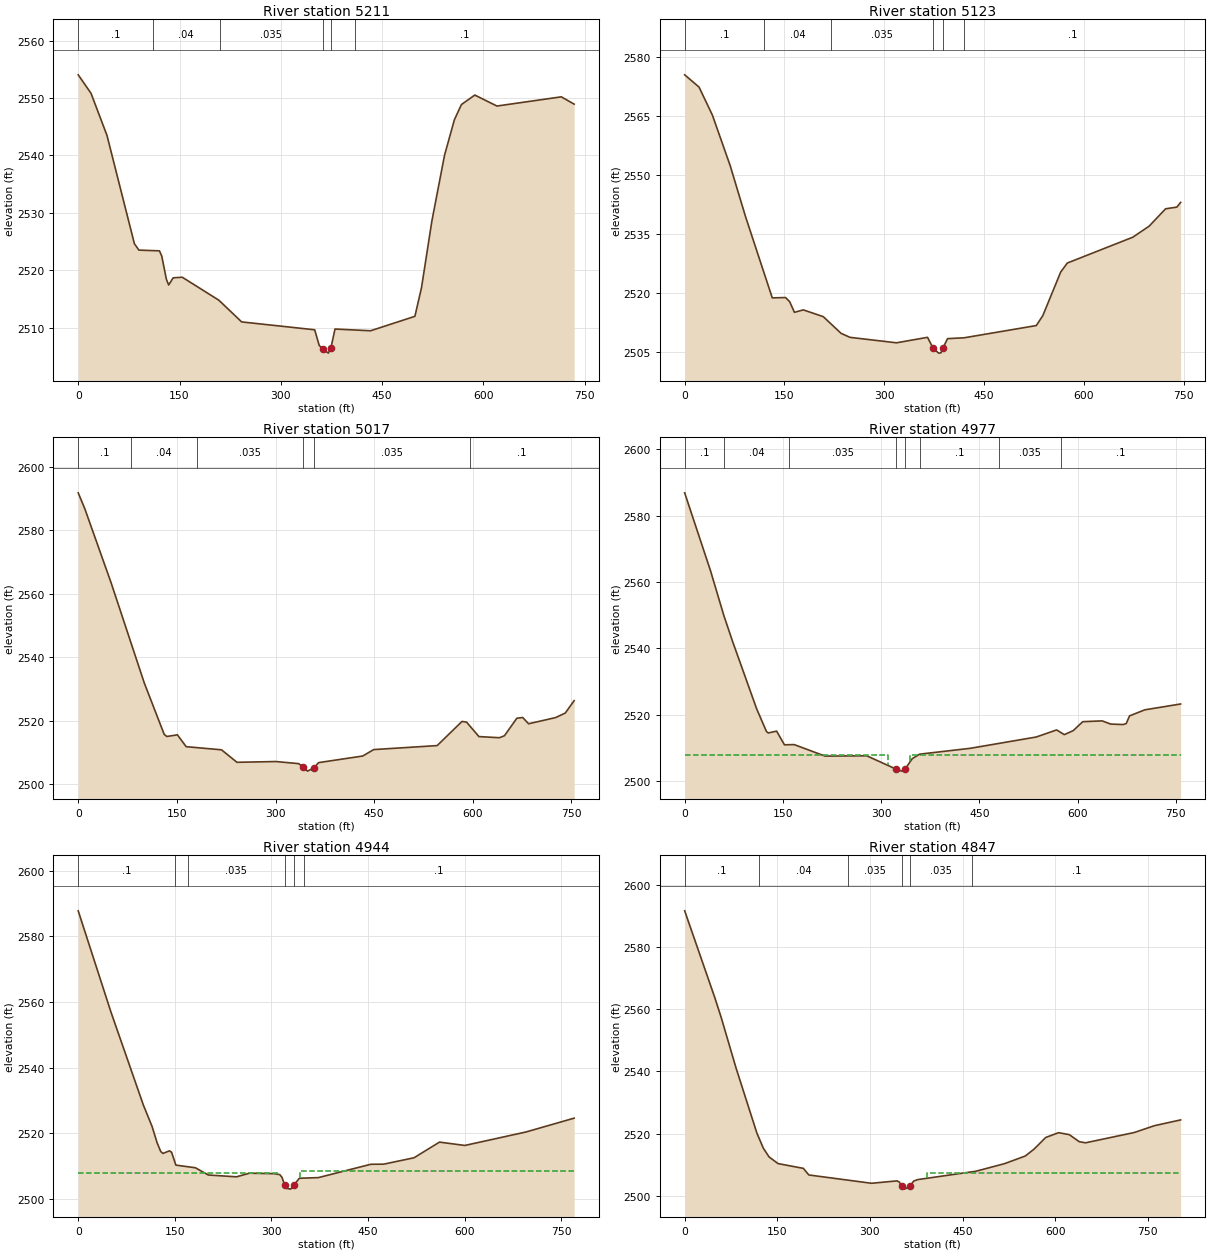
Type RM Length L Ch R = 1 ,5211    ,86.8,87.9,86.6
XS GIS Cut Line= 3
     2153721.624      236111.665     2154081.357      236023.034
     2154444.707      236005.639
#Sta/Elev= 30
       0 2554.03      19 2550.81    42.6 2543.49    83.2 2524.65    89.9 2523.54
   120.3 2523.41   123.7 2522.51   130.5  2518.5   133.9 2517.47   140.6 2518.72
   154.1 2518.82   208.2 2514.83     242 2511.05   350.1 2509.68   356.9 2506.94
     362 2506.37   370.4 2505.62   374.2 2506.54   380.2 2509.81   432.9 2509.51
   498.5 2512.02   508.3 2517.01   523.6 2528.57   542.4 2540.05     557 2546.22
   567.4 2548.86   587.2 2550.51     620  2548.6   715.3  2550.2   734.3 2548.93
#Mann= 6 ,-1 , 0
       0      .1       0     110     .04       0     210    .035       0
     362    .045       0   374.2    .035       0  410.49      .1       0
Bank Sta=362,374.2
XS Rating Curve= 0 ,0
Exp/Cntr=0.3,0.1

Type RM Length L Ch R = 1 ,5123    ,105.7,105.5,104.9
XS GIS Cut Line= 3
2153712.25772297236179.3817679832154278.40111655236075.477803984
2154436.92126675236014.201107267
#Sta/Elev= 30
       0  2575.4    21.6 2572.29    41.6  2565.2    68.3  2552.4    91.6 2539.34
   131.7 2518.76   151.7 2518.84   157.9 2517.78     165 2515.09   178.4 2515.71
   208.4 2513.99   235.1 2509.76   248.4 2508.74   318.4 2507.35   365.1 2508.74
   373.52505.968   381.8 2504.73   385.2 2504.79   388.62506.142   395.2 2508.41
     420 2508.62   528.6 2511.73   538.4 2514.24   565.3 2525.32   575.3 2527.61
   673.8 2534.17   698.4 2536.99     723 2541.38   739.9 2541.81   745.6    2543
#Mann= 6 ,-1 , 0
       0      .1       0     120     .04       0     220    .035       0
   373.5    .045       0   388.6    .035       0     420      .1       0
Bank Sta=373.5,388.6
XS Rating Curve= 0 ,0
Exp/Cntr(USF)=0,0
Exp/Cntr=0.3,0.1

Type RM Length L Ch R = 1 ,5017    ,40.5,40.4,40.3
XS GIS Cut Line= 3
2153750.04883612236288.402249193 2154283.1840717236174.783264561
 2154437.5893585236033.973411813
#Sta/Elev= 30
       0 2591.82     9.9 2586.89    50.2 2563.36   100.5 2531.87   130.7 2515.72
   134.7 2515.02   150.8 2515.54   164.2 2511.81   217.9 2510.82   241.4 2506.88
   300.6 2507.12   335.3 2506.46   341.12505.525   348.7  2504.1   358.5 2505.15
   365.5 2506.78   432.6 2508.86   449.3 2510.89   545.8 2512.15   583.6 2519.77
   590.6 2519.53   609.3 2514.99   640.4 2514.63   648.1 2515.25     667 2520.78
   675.9    2521   684.8 2519.03     726 2520.98   740.6 2522.41   754.1 2526.31
#Mann= 6 ,-1 , 0
       0      .1       0      80     .04       0     180    .035       0
   341.1    .045       0   358.5    .035       0  595.11      .1       0
Bank Sta=341.1,358.5
XS Rating Curve= 0 ,0
Exp/Cntr(USF)=0,0
Exp/Cntr=0.5,0.3

Type RM Length L Ch R = 1 ,4977    ,33.3,33.3,33.3
XS GIS Cut Line= 3
     2153773.598      236327.288     2154286.619      236213.573
      2154447.21      236046.038
#Sta/Elev= 30
       0 2586.85    39.6  2563.3    59.7 2549.98    73.2 2542.08   110.1 2521.72
   124.9 2514.99   127.6 2514.53   140.4 2515.09   152.4 2510.97   167.3 2511.03
   214.3 2507.57   278.2 2507.65   322.72503.666   331.9 2503.04   336.8  2503.7
   347.7 2506.81     359 2508.15   436.1 2509.91   536.9 2513.31   568.1 2515.45
   579.9 2514.03   593.5 2515.24     608 2517.93   637.7 2518.17   650.7 2517.21
   669.6 2517.07   674.4 2517.35   679.5 2519.68   702.8  2521.5   757.5 2523.26
#Mann= 8 ,-1 , 0
       0      .1       0      60     .04       0     160    .035       0
   322.7    .045       0   336.8    .035       0     360      .1       0
     480    .035       0  575.47      .1       0
#XS Ineff= 2 , 0
          310.13 2507.92  344.77         2507.76
Permanent Ineff=
       F       F
Bank Sta=322.7,336.8
XS Rating Curve= 0 ,0
Exp/Cntr=0.5,0.3

Type RM Length L Ch R = 1 ,4944    ,99.5,96.4,92.6
XS GIS Cut Line= 3
     2153782.279      236359.406       2154295.3      236245.691
     2154464.571      236069.476
#Sta/Elev= 30
       0 2587.76    50.8 2556.93   101.2 2528.54   114.7 2522.02   122.5 2517.06
   128.1  2514.4   131.5 2513.83   141.6 2514.62   144.9  2514.2   151.6 2510.27
   181.9 2509.46   202.1 2507.25   245.7  2506.7   265.9  2507.8   304.1 2507.66
   312.9 2507.37   316.3 2506.54   320.62504.141     323 2503.21   329.8 2502.95
   334.42504.097   343.2 2506.26   372.8 2506.46   454.1 2510.52   474.3 2510.56
   521.3 2512.51   560.8 2517.28   600.1 2516.26   694.8 2520.35   769.8 2524.58
#Mann= 6 ,-1 , 0
       0      .1       0     150     .04       0     170    .035       0
   320.6    .045       0   334.4    .035       0     350      .1       0
#XS Ineff= 2 , 0
          311.97 2508.01  344.84         2508.39
Permanent Ineff=
       F       F
Bank Sta=320.6,334.4
XS Rating Curve= 0 ,0
Exp/Cntr=0.5,0.3

Type RM Length L Ch R = 1 ,4847    ,79.6,75.6,69.3
XS GIS Cut Line= 4
2153813.81851573236508.0502619442153983.22194011236463.811151119
2154259.44663209236308.4347618792154465.53614838 236075.37017802
#Sta/Elev= 30
       0 2591.58      49 2563.59    59.4 2557.16    83.1 2541.16     117 2520.16
   127.5 2515.31   136.7 2512.54   151.2  2510.4   192.2 2508.87     201 2506.75
   302.6 2504.08     344 2504.85   347.8 2504.43   351.62503.088   356.1  2502.2
   364.7 2503.15   370.8 2504.78   377.4 2505.26   471.7 2507.95   517.8 2510.37
   551.4 2512.82   565.4 2514.98   584.6 2518.78   605.4 2520.33   622.9 2519.69
     639 2517.43   649.2 2517.08     728 2520.38   760.6 2522.57   803.1 2524.43
#Mann= 6 ,-1 , 0
       0      .1       0     120     .04       0  265.08    .035       0
   351.6    .045       0   364.7    .035       0  465.08      .1       0
#XS Ineff= 2 , 0
                          392.11         2507.36
Permanent Ineff=
       F       F
Bank Sta=351.6,364.7
XS Rating Curve= 0 ,0
Exp/Cntr(USF)=0,0
Exp/Cntr=0.3,0.1

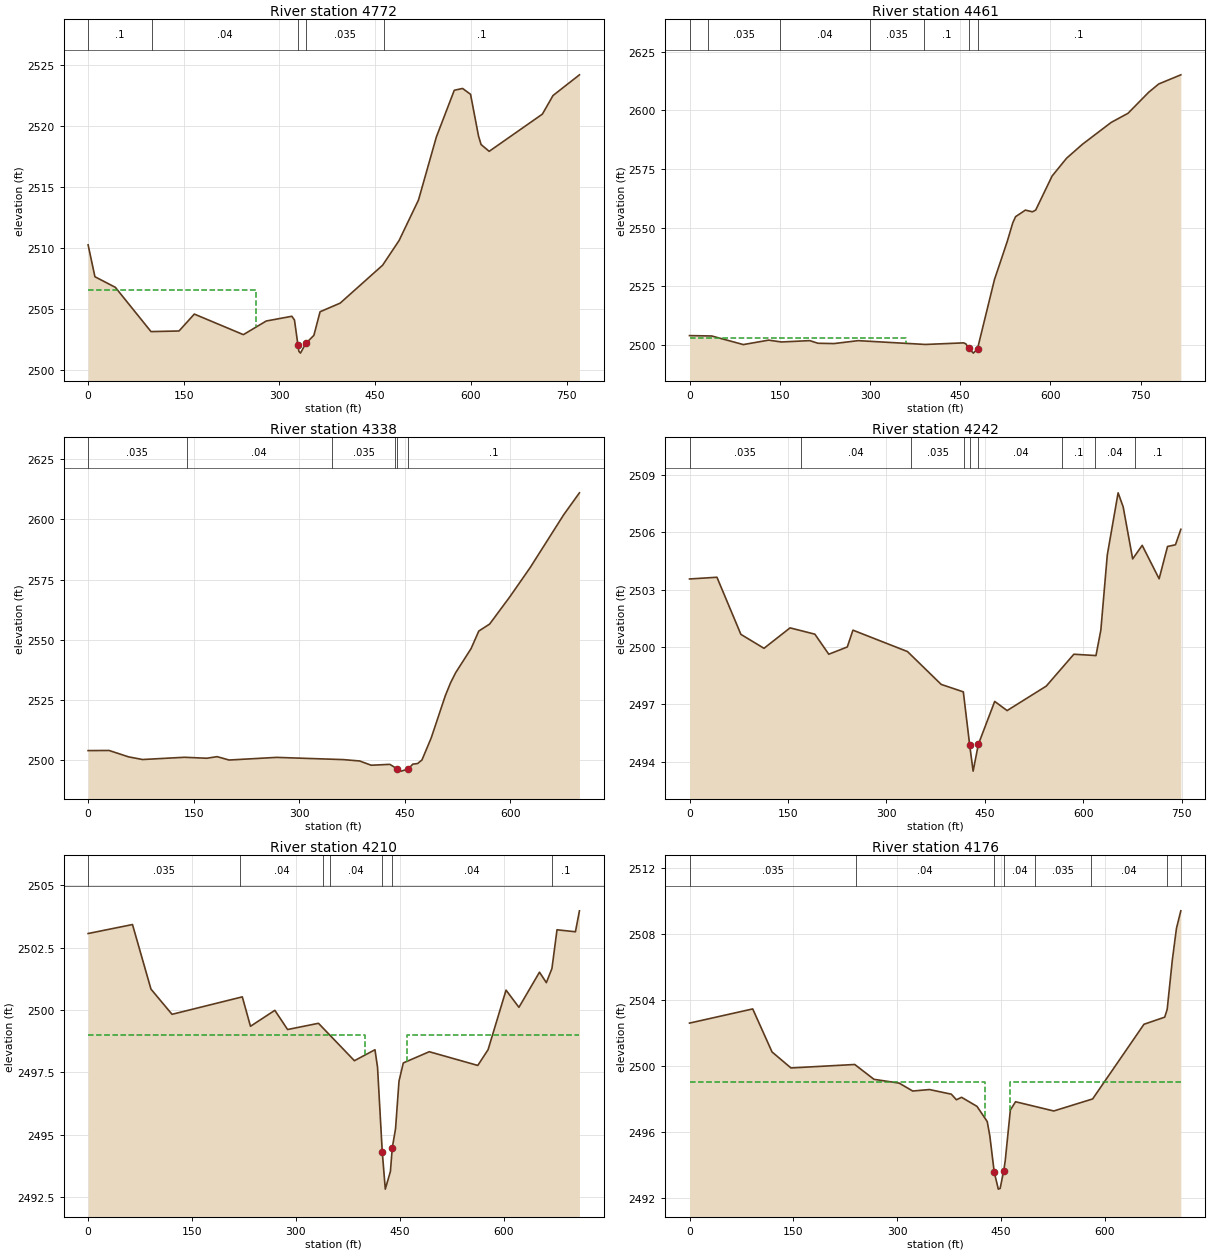
Type RM Length L Ch R = 1 ,4772    ,304.4,310.8,313.1
XS GIS Cut Line= 3
       2154007.2      236698.182     2154220.662      236391.073
     2154465.258      236079.352
#Sta/Elev= 30
       0 2510.25    10.7 2507.63    42.7 2506.76    98.6 2503.12   142.5 2503.17
   166.5 2504.56   243.4 2502.87   279.2 2503.99   319.4 2504.38   323.5 2504.07
   328.92502.037   330.3 2501.51   332.9 2501.35   341.22502.143   353.9 2502.81
   363.6 2504.75   395.1 2505.46   461.7 2508.58   487.5 2510.61   517.9 2513.94
   545.9 2519.12     574 2522.96     587 2523.11   599.5 2522.63     612  2519.2
     616  2518.5   628.7 2517.94   712.1    2521   728.8 2522.53   770.2 2524.23
#Mann= 5 ,-1 , 0
       0      .1       0     100     .04       0   328.9    .045       0
   341.2    .035       0  464.01      .1       0
#XS Ineff= 2 , 0
          263.05  2506.5
Permanent Ineff=
       F       F
Bank Sta=328.9,341.2
XS Rating Curve= 0 ,0
Exp/Cntr=0.3,0.1

Type RM Length L Ch R = 1 ,4461    ,115.2,122.7,130.7
XS GIS Cut Line= 3
     2154093.226       236785.06      2154485.44      236522.891
     2154756.419       236309.39
#Sta/Elev= 30
       0 2503.84    36.9 2503.68    89.5 2500.01   131.6 2501.91   152.6 2501.12
   199.9  2501.7   213.5 2500.57   240.3 2500.44   280.3 2501.69   392.1 2500.06
   455.5 2500.74   459.2 2500.36   464.32498.403   471.8 2496.36   478.72498.212
   506.9 2527.78     528 2543.94   537.3 2551.97     542 2554.64   558.3 2557.43
     570 2556.71   575.4 2557.44   602.7 2571.99   626.8  2579.6   653.3 2585.58
   700.8 2594.86   728.9 2598.78   763.3 2607.77     780  2611.3   816.7  2615.2
#Mann= 7 ,-1 , 0
       0      .1       0      30    .035       0     150     .04       0
     300    .035       0     390      .1       0   464.3    .045       0
   478.7      .1       0
#XS Ineff= 2 , 0
          359.15 2503.03
Permanent Ineff=
       F       F
Bank Sta=464.3,478.7
XS Rating Curve= 0 ,0
Exp/Cntr=0.3,0.1

Type RM Length L Ch R = 1 ,4338    ,90.7,96.3,102.1
XS GIS Cut Line= 4
2154125.49554283236791.648221292 2154362.3136944236630.315855541
 2154578.4102577236634.7561958832154754.54375792236548.909615941
#Sta/Elev= 30
       0 2503.97    29.8 2504.03    57.6 2501.37    77.5 2500.27     137  2501.2
   168.8  2500.8   183.4 2501.46   200.5 2500.06     268 2501.16   363.1 2500.23
   386.1 2499.66   402.5  2497.9   429.1 2498.26   438.8 2496.51   445.2 2495.45
   455.1 2496.31   461.6 2498.34   468.5  2498.6   474.7 2500.09   487.8 2509.21
     508 2526.87   515.3 2532.08   522.6 2536.32   544.5 2546.32   555.5 2553.61
   570.9 2556.51   599.3  2567.7   628.5 2579.94   676.4 2601.99   698.6    2611
#Mann= 6 ,-1 , 0
       0    .035       0     140     .04       0  346.55    .035       0
  436.55      .1       0   438.8    .045       0   455.1      .1       0
Bank Sta=438.8,455.1
XS Rating Curve= 0 ,0
Exp/Cntr(USF)=0,0
Exp/Cntr=0.3,0.1

Type RM Length L Ch R = 1 ,4242    ,31.4,32,32
XS GIS Cut Line= 3
2154137.51932665236815.5660323152154363.03089159236652.636624154
2154775.20992415236879.227191795
#Sta/Elev= 30
       0 2503.56    41.8 2503.65    78.3 2500.66   113.5 2499.93   153.2    2501
     191 2500.67   212.2 2499.62   240.4    2500     249 2500.88   332.1 2499.76
   383.5 2498.04   417.2 2497.65   426.92494.855   432.1  2493.5   440.12494.904
     465 2497.15   483.9 2496.67   543.5 2497.95   585.6 2499.62   619.3 2499.55
   626.7 2500.88   636.5 2504.81     653 2508.07   660.7 2507.34   675.2 2504.61
   689.7 2505.32   715.5 2503.57   728.3 2505.26   740.4 2505.35   748.6 2506.16
#Mann= 9 ,-1 , 0
       0    .035       0     170     .04       0  338.21    .035       0
  418.21     .04       0   426.9    .045       0   440.1     .04       0
  568.21      .1       0  618.21     .04       0  678.21      .1       0
Bank Sta=426.9,440.1
XS Rating Curve= 0 ,0
Exp/Cntr(USF)=0,0
Exp/Cntr=0.5,0.3

Type RM Length L Ch R = 1 ,4210    ,35.2,34.4,34.5
XS GIS Cut Line= 3
      2154134.71      236835.969     2154356.932      236683.191
     2154745.821       236888.92
#Sta/Elev= 30
       0 2503.07    64.1 2503.43    90.8 2500.84   121.2 2499.83   222.7 2500.53
   234.5 2499.35   269.7 2499.99   288.1 2499.22   332.7 2499.47   384.6 2497.97
   414.3 2498.41     418 2497.71   424.82494.324   429.2 2492.82   436.6 2493.53
   439.3 2494.48     444 2495.24     449 2497.15   455.2 2497.88   492.7 2498.33
   562.8 2497.78   577.6 2498.41   603.6  2500.8   622.2 2500.11   651.9 2501.52
   661.8  2501.1   669.9 2501.67   677.2 2503.22   703.8 2503.14   709.6 2503.98
#Mann= 7 ,-1 , 0
       0    .035       0     220     .04       0  339.67    .035       0
  349.67     .04       0   424.8    .045       0   439.3     .04       0
  669.67      .1       0
#XS Ineff= 2 , 0
             400    2499     460            2499
Permanent Ineff=
       F       F
Bank Sta=424.8,439.3
XS Rating Curve= 0 ,0
Exp/Cntr=0.5,0.3

Type RM Length L Ch R = 1 ,4176    ,56.8,54.7,52.1
XS GIS Cut Line= 3
     2154120.821      236863.746     2154343.043      236710.969
     2154731.932      236916.698
#Sta/Elev= 30
       0  2502.6    91.3 2503.46   119.2 2500.85   146.5 2499.88   238.6 2500.09
   266.5 2499.19   302.8 2498.96   322.4 2498.48   346.5 2498.57   378.1 2498.29
   385.5 2497.95   392.9  2498.1   415.2 2497.55     430 2496.63   433.7 2495.77
   440.12493.567     446 2492.53   448.6 2492.57   453.82493.636     456 2494.26
   463.4 2497.33   470.9 2497.83   526.1 2497.27   582.2    2498   656.4 2502.53
   686.3 2502.96   689.9 2503.43   697.3 2506.42   703.3 2508.35   709.6 2509.41
#Mann= 8 ,-1 , 0
       0    .035       0     240     .04       0   440.1    .045       0
   453.8     .04       0  499.67    .035       0  579.67     .04       0
  689.67      .1       0  709.63     .04       0
#XS Ineff= 2 , 0
           426.7    2499   463.3            2499
Permanent Ineff=
       F       F
Bank Sta=440.1,453.8
XS Rating Curve= 0 ,0
Exp/Cntr=0.5,0.3

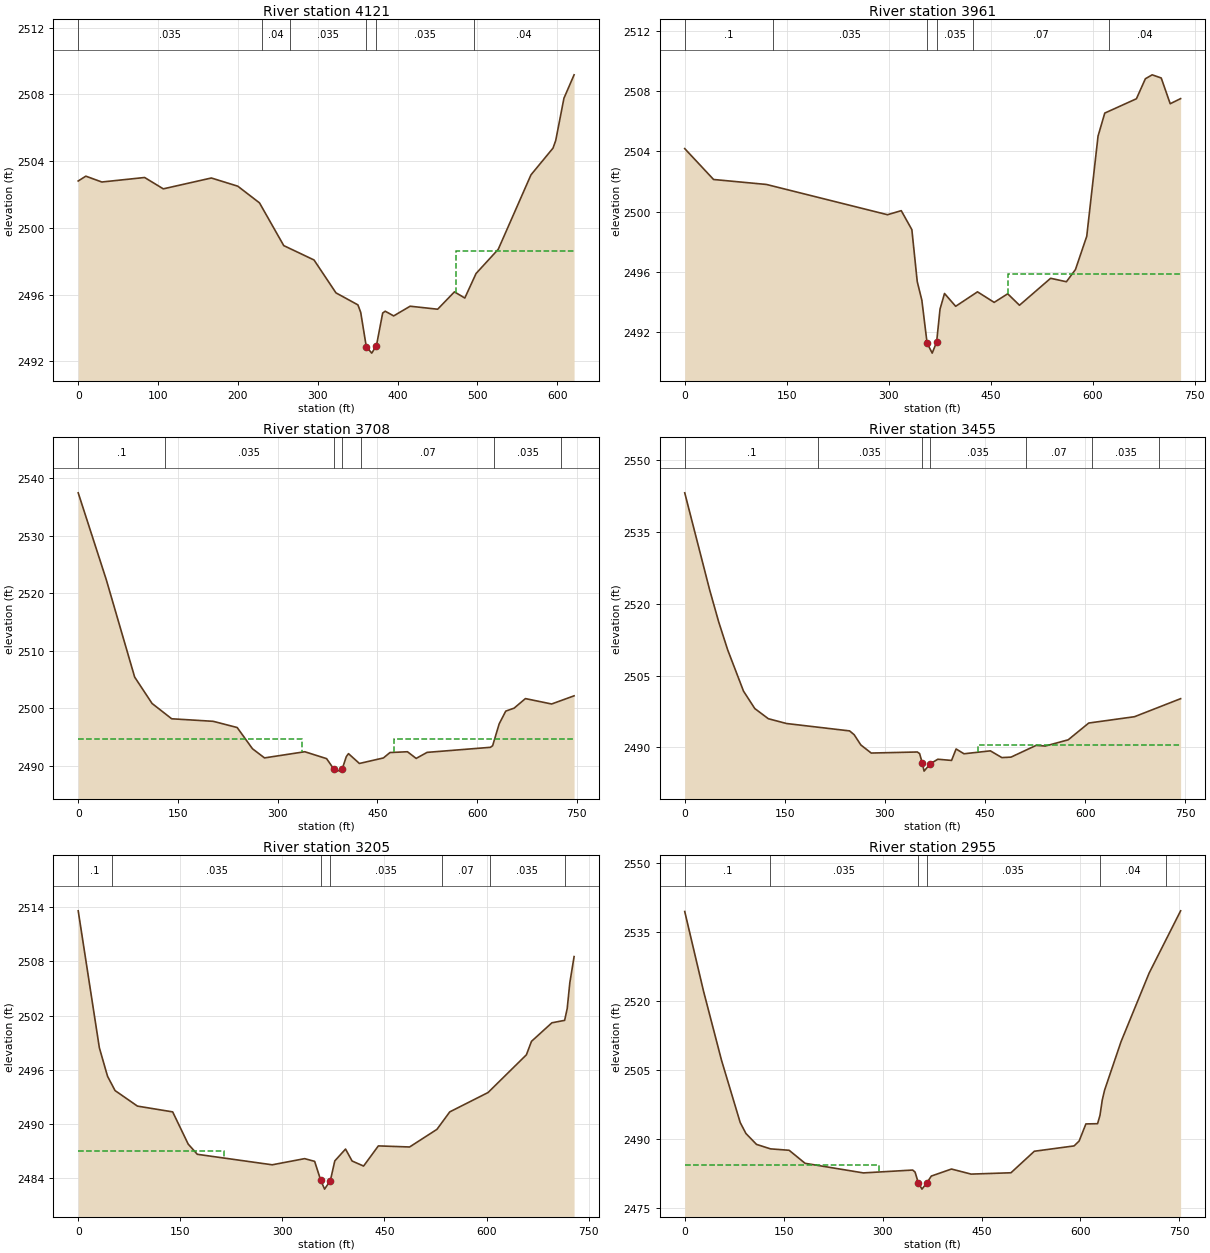
Type RM Length L Ch R = 1 ,4121    ,160.8,159.9,158
XS GIS Cut Line= 3
2154137.51932665 236859.805143142154378.13692943236811.250021502
2154736.36582684236924.545305323
#Sta/Elev= 30
       0 2502.81     9.5  2503.1    29.6 2502.75    83.2 2503.02   106.6 2502.34
   166.8 2502.99   199.9  2502.5   227.1  2501.5   257.5 2498.94   295.4 2498.08
   322.9 2496.11   350.4 2495.39   353.9 2494.94   360.92492.883   367.7  2492.5
   373.62492.947   381.4  2494.9   384.6 2495.01   395.2 2494.73   415.8 2495.31
   450.3 2495.13   471.3 2496.17   484.3  2495.8   498.4 2497.27   526.2 2498.72
   567.2 2503.18   594.8 2504.78   598.2 2505.24   608.5 2507.77   621.2 2509.17
#Mann= 6 ,-1 , 0
       0    .035       0     230     .04       0  265.47    .035       0
   360.9    .045       0   373.6    .035       0  495.47     .04       0
#XS Ineff= 2 , 0
                          473.03         2498.61
Permanent Ineff=
       F       F
Bank Sta=360.9,373.6
XS Rating Curve= 0 ,0
Exp/Cntr(USF)=0,0
Exp/Cntr=0.3,0.1

Type RM Length L Ch R = 1 ,3961    ,255.1,252.7,250
XS GIS Cut Line= 3
     2154098.974      236921.673     2154453.714      237002.296
     2154814.845      237056.723
#Sta/Elev= 30
       0 2504.18    42.4 2502.13   120.1  2501.8   298.1 2499.79   318.3 2500.06
   333.9  2498.8   341.8 2495.35   348.6 2494.11   356.32491.263   363.8  2490.6
   370.32491.334   375.3 2493.52   381.9 2494.56   398.3 2493.71   430.4 2494.67
   454.9 2493.97   474.8 2494.54   492.1 2493.78   537.9 2495.57   561.1 2495.34
   574.4 2496.15     591 2498.36   607.6 2505.01   617.5 2506.54     664 2507.49
   677.2 2508.82   687.2 2509.08   700.5 2508.87   713.7 2507.16     729  2507.5
#Mann= 6 ,-1 , 0
       0      .1       0     130    .035       0   356.3    .045       0
   370.3    .035       0  423.79     .07       0  623.79     .04       0
#XS Ineff= 2 , 0
                          474.74         2495.83
Permanent Ineff=
       F       F
Bank Sta=356.3,370.3
XS Rating Curve= 0 ,0
Exp/Cntr=0.3,0.1

Type RM Length L Ch R = 1 ,3708    ,254,253,248.9
XS GIS Cut Line= 3
     2154088.284      237235.797     2154473.815      237244.807
     2154833.548      237226.819
#Sta/Elev= 30
       0 2537.45    42.2 2522.36    84.9 2505.42   111.1 2500.83   140.6 2498.17
     203 2497.73   239.1 2496.65   262.1 2492.96   280.2 2491.37   340.8 2492.44
   373.6 2491.24     3842489.498   393.3 2489.07   397.12489.447   403.2 2491.59
   406.5 2492.11   422.9  2490.4     459 2491.36   468.9  2492.3   495.2 2492.44
   508.3 2491.28   524.7 2492.33     620 2493.21   623.3 2493.49   633.1 2497.28
     643  2499.5   655.6 2500.02   672.6 2501.68     712 2500.74   745.8 2502.16
#Mann= 7 ,-1 , 0
       0      .1       0     130    .035       0     384    .045       0
   397.1    .035       0  425.64     .07       0  625.64    .035       0
  725.64     .04       0
#XS Ineff= 2 , 0
          336.84 2494.59  475.54         2494.59
Permanent Ineff=
       F       F
Bank Sta=384,397.1
XS Rating Curve= 0 ,0
Exp/Cntr=0.3,0.1

Type RM Length L Ch R = 1 ,3455    ,251,250,246.6
XS GIS Cut Line= 3
     2154123.782      237560.104     2154473.601       237472.03
     2154839.676      237361.143
#Sta/Elev= 30
       0  2543.1    37.3 2522.88    50.9 2516.18    64.4 2510.34    88.1 2501.74
     105 2498.11   125.3 2495.99   152.5 2494.99   247.1 2493.45   253.9 2492.66
     264 2490.51   279.5 2488.83   348.6 2489.05     352 2488.72   356.22486.672
   358.7 2485.06   368.22486.606   379.3 2487.54   399.9 2487.29   406.7 2489.68
   418.5 2488.68   458.1 2489.29   475.3 2487.88     489 2487.98   526.7 2490.43
   540.4 2490.29   574.7 2491.59   605.5 2495.09   674.1 2496.41   743.2 2500.17
#Mann= 7 ,-1 , 0
       0      .1       0     200    .035       0   356.2    .045       0
   368.2    .035       0  510.74     .07       0  610.74    .035       0
  710.74     .04       0
#XS Ineff= 2 , 0
                          438.95         2490.42
Permanent Ineff=
       F       F
Bank Sta=356.2,368.2
XS Rating Curve= 0 ,0
Exp/Cntr=0.3,0.1

Type RM Length L Ch R = 1 ,3205    ,247.8,250,250.3
XS GIS Cut Line= 3
     2154275.664       237844.22     2154602.098      237681.403
     2154920.171      237504.697
#Sta/Elev= 30
       0 2513.58    31.1 2498.43    43.1 2495.29    54.1 2493.71      87 2491.99
   138.8 2491.35   161.6 2487.79     175 2486.66     285  2485.5   332.7 2486.18
   347.4 2485.88   356.32483.797     362 2482.81   370.52483.759     377 2485.93
   392.8 2487.24   402.4 2485.92   419.3 2485.36     441 2487.59   486.9 2487.47
   527.1 2489.42   545.9 2491.35   602.2 2493.49   658.5 2497.66     666 2499.15
     696  2501.2   714.7 2501.47   718.5 2502.78   722.3 2505.61   728.6 2508.52
#Mann= 7 ,-1 , 0
       0      .1       0      50    .035       0   356.3    .045       0
   370.5    .035       0  534.79     .07       0  604.79    .035       0
  714.79     .04       0
#XS Ineff= 2 , 0
          214.74 2487.04
Permanent Ineff=
       F       F
Bank Sta=356.3,370.5
XS Rating Curve= 0 ,0
Exp/Cntr=0.3,0.1

Type RM Length L Ch R = 1 ,2955    ,273,273.7,272.8
XS GIS Cut Line= 3
     2154331.259      238042.778      2154664.49      237909.487
     2155027.678       237759.61
#Sta/Elev= 30
       0 2539.43    28.5 2522.14    55.8 2507.13    84.1 2493.63    92.8 2491.25
   108.8 2488.89     130 2487.92   158.3 2487.61   182.5 2484.78   270.8  2482.7
   345.6 2483.32   349.2 2482.88   354.22480.516   359.7 2479.18   367.22480.585
   373.9 2482.02   404.4 2483.54   434.2 2482.44   494.6 2482.73     530  2487.4
   590.3 2488.56   597.9 2489.61   608.2 2493.33   625.9 2493.38   629.5 2495.17
     633 2498.51   636.5 2500.65   661.4 2511.16     704 2526.05   751.8 2539.58
#Mann= 6 ,-1 , 0
       0      .1       0     130    .035       0   354.2    .045       0
   367.2    .035       0   628.9     .04       0   728.9      .1       0
#XS Ineff= 2 , 0
          295.05 2484.37
Permanent Ineff=
       F       F
Bank Sta=354.2,367.2
XS Rating Curve= 0 ,0
Exp/Cntr=0.3,0.1

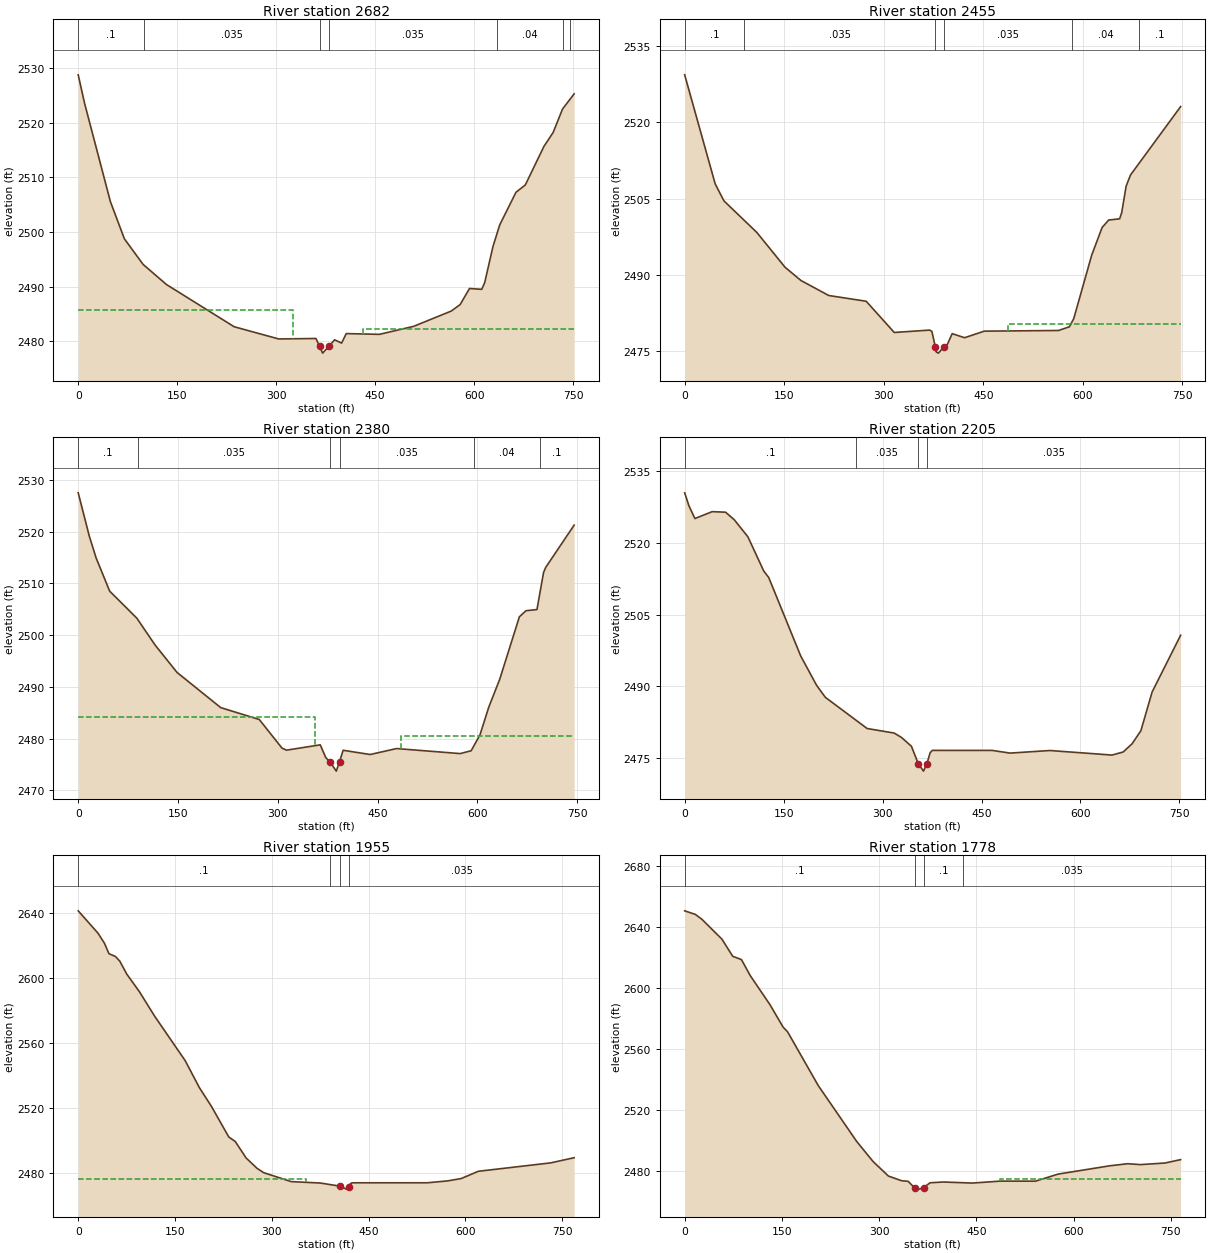
Type RM Length L Ch R = 1 ,2682    ,220.5,226.3,230.7
XS GIS Cut Line= 3
     2154423.202      238271.585     2154761.375      238134.434
     2155121.297      237993.261
#Sta/Elev= 30
       0 2528.79     9.8  2523.5    48.8 2505.55      70 2498.74    98.3 2494.06
   133.7 2490.37   236.4 2482.63   303.7  2480.4   360.3 2480.48   365.7 2479.04
   370.4  2477.8     3802479.076   388.5 2480.24   399.1 2479.64   406.2 2481.38
   456.4 2481.24   508.4 2482.71   565.3 2485.51   578.8  2486.7   592.9 2489.64
   611.5 2489.49   615.9  2490.7   628.5 2497.33   638.7 2501.29   663.4 2507.28
   677.5 2508.61   705.7 2515.67   719.7 2518.23   733.9 2522.53   751.5  2525.3
#Mann= 7 ,-1 , 0
       0      .1       0     100    .035       0   365.7    .045       0
     380    .035       0  634.93     .04       0  734.93    .035       0
  744.93      .1       0
#XS Ineff= 2 , 0
          325.42 2485.79  431.14         2482.13
Permanent Ineff=
       F       F
Bank Sta=365.7,380
XS Rating Curve= 0 ,0
Exp/Cntr=0.3,0.1

Type RM Length L Ch R = 1 ,2455    ,73.4,75.2,77.5
XS GIS Cut Line= 3
      2154422.65      238285.244     2154804.616      238324.145
     2155167.029      238350.018
#Sta/Elev= 30
       0 2529.32      46 2507.87    59.2 2504.53   108.6 2498.35   151.2 2491.49
   175.2 2488.88   217.1 2485.93   273.5  2484.8   315.8 2478.66   369.2 2479.13
   372.5 2478.87   377.82475.765   379.1 2474.82   382.4  2474.6   390.52475.846
   395.5 2476.23   403.1 2478.43   421.8 2477.63   451.4 2478.92   563.3 2479.05
   579.7 2479.78   586.3  2481.4   613.4  2493.9     629  2499.3   638.9 2500.77
   655.4 2501.01   658.6 2502.26   665.2 2507.43   671.8 2509.63   747.3 2523.07
#Mann= 6 ,-1 , 0
       0      .1       0      90    .035       0   377.8    .045       0
   390.5    .035       0  583.94     .04       0  683.94      .1       0
#XS Ineff= 2 , 0
                          487.37         2480.38
Permanent Ineff=
       F       F
Bank Sta=377.8,390.5
XS Rating Curve= 0 ,0
Exp/Cntr=0.3,0.1

Type RM Length L Ch R = 1 ,2380    ,172.2,174.8,173.5
XS GIS Cut Line= 3
2154426.13858504238293.7871864632154844.55185545238411.278591908
2155153.86596366238443.648673001
#Sta/Elev= 30
       0  2527.5    16.6 2519.17    26.8 2514.96    47.3  2508.5    88.2 2503.27
   115.4 2498.12   148.6 2492.79   214.3 2485.99   272.2  2483.7   306.3 2478.18
   313.1 2477.77   363.9  2478.8   372.1 2476.35   378.6 2475.49     388 2473.72
   392.92475.565   398.3 2477.75   438.9 2476.93   478.6 2478.08   574.3 2477.11
   590.8 2477.66     604 2480.72   617.2 2486.07   633.7 2491.47   663.3 2503.55
   673.2 2504.72   689.7 2504.94   699.6 2512.11   702.9  2513.1   745.6 2521.26
#Mann= 6 ,-1 , 0
       0      .1       0      90    .035       0   378.6    .045       0
   392.9    .035       0   594.6     .04       0   694.6      .1       0
#XS Ineff= 2 , 0
          355.25 2484.11  485.42         2480.56
Permanent Ineff=
       F       F
Bank Sta=378.6,392.9
XS Rating Curve= 0 ,0
Exp/Cntr(USF)=0,0
Exp/Cntr=0.3,0.1

Type RM Length L Ch R = 1 ,2205    ,250.8,250,247.2
XS GIS Cut Line= 3
     2154389.119      238374.298      2154704.79      238544.959
     2155088.106      238631.483
#Sta/Elev= 30
       0 2530.48     6.3 2527.82    15.5  2525.1    41.6 2526.54      62 2526.43
    75.2 2524.85    95.9 2521.27   119.9 2514.12   127.4 2512.78   175.9 2496.36
     200 2490.22   213.2 2487.72   276.6 2481.19   317.6 2480.24   328.8 2479.31
   343.7 2477.49     3542473.869     362 2472.28   367.22473.833   372.1 2476.13
   375.5 2476.62   466.3 2476.61   493.2 2476.05   553.7 2476.59   647.8 2475.64
   664.7 2476.28   678.2 2477.99   691.6 2480.74   708.6 2488.83   751.8 2500.69
#Mann= 4 ,-1 , 0
       0      .1       0     260    .035       0     354    .045       0
   367.2    .035       0
Bank Sta=354,367.2
XS Rating Curve= 0 ,0
Exp/Cntr=0.3,0.1

Type RM Length L Ch R = 1 ,1955    ,176.2,177.6,178
XS GIS Cut Line= 3
     2154330.336      238685.154     2154731.823         238784.
     2155085.329      238819.347
#Sta/Elev= 30
       0 2641.32    30.7 2627.56    40.8 2621.29    47.6 2614.96    57.7 2613.24
    64.5 2610.34    75.3 2602.37    94.9 2591.55   118.5 2576.48   165.8 2549.15
   187.9 2532.47   206.4 2521.08   233.4 2502.15   243.4 2499.42   260.4 2489.18
   277.3 2482.86   287.5 2480.21   330.2 2474.71   375.3 2473.84     406 2471.91
   415.8 2470.09   419.32471.687   422.4 2473.65   425.7 2473.98   541.1 2473.99
   573.2 2475.18   593.8 2476.62   620.2 2481.07   732.3 2486.24   768.7 2489.42
#Mann= 4 ,-1 , 0
       0      .1       0     390    .035       0     406    .045       0
   419.3    .035       0
#XS Ineff= 2 , 0
           353.5 2476.51
Permanent Ineff=
       F       F
Bank Sta=406,419.3
XS Rating Curve= 0 ,0
Exp/Cntr=0.3,0.1

Type RM Length L Ch R = 1 ,1778    ,95.3,94.9,94.6
XS GIS Cut Line= 2
2154294.88630402238804.2735954692155036.58759815238991.754632123
#Sta/Elev= 30
       0  2650.8    16.5 2648.45    26.7 2645.22    57.5 2632.21    74.1    2621
    87.6 2618.82   101.1 2608.36   131.6 2589.26   151.9 2574.51   158.7 2571.52
     206 2536.26   265.4 2499.57   290.6 2486.44   314.3 2476.91   334.6 2473.85
   344.8 2473.45   354.6 2469.14   361.7 2468.34   368.5 2469.38   378.6  2472.5
   398.9 2473.01   443.7 2472.31   486.9 2473.59   541.1 2473.55   576.1  2478.2
   656.1 2483.66   683.2 2484.99     703 2484.42   740.7 2485.45     765 2487.67
#Mann= 4 ,-1 , 0
       0      .1       0   354.6    .045       0   368.5      .1       0
     430    .035       0
#XS Ineff= 2 , 0
                          486.69         2474.66
Permanent Ineff=
       F       F
Bank Sta=354.6,368.5
XS Rating Curve= 0 ,0
Exp/Cntr(USF)=0,0
Exp/Cntr=0.3,0.1