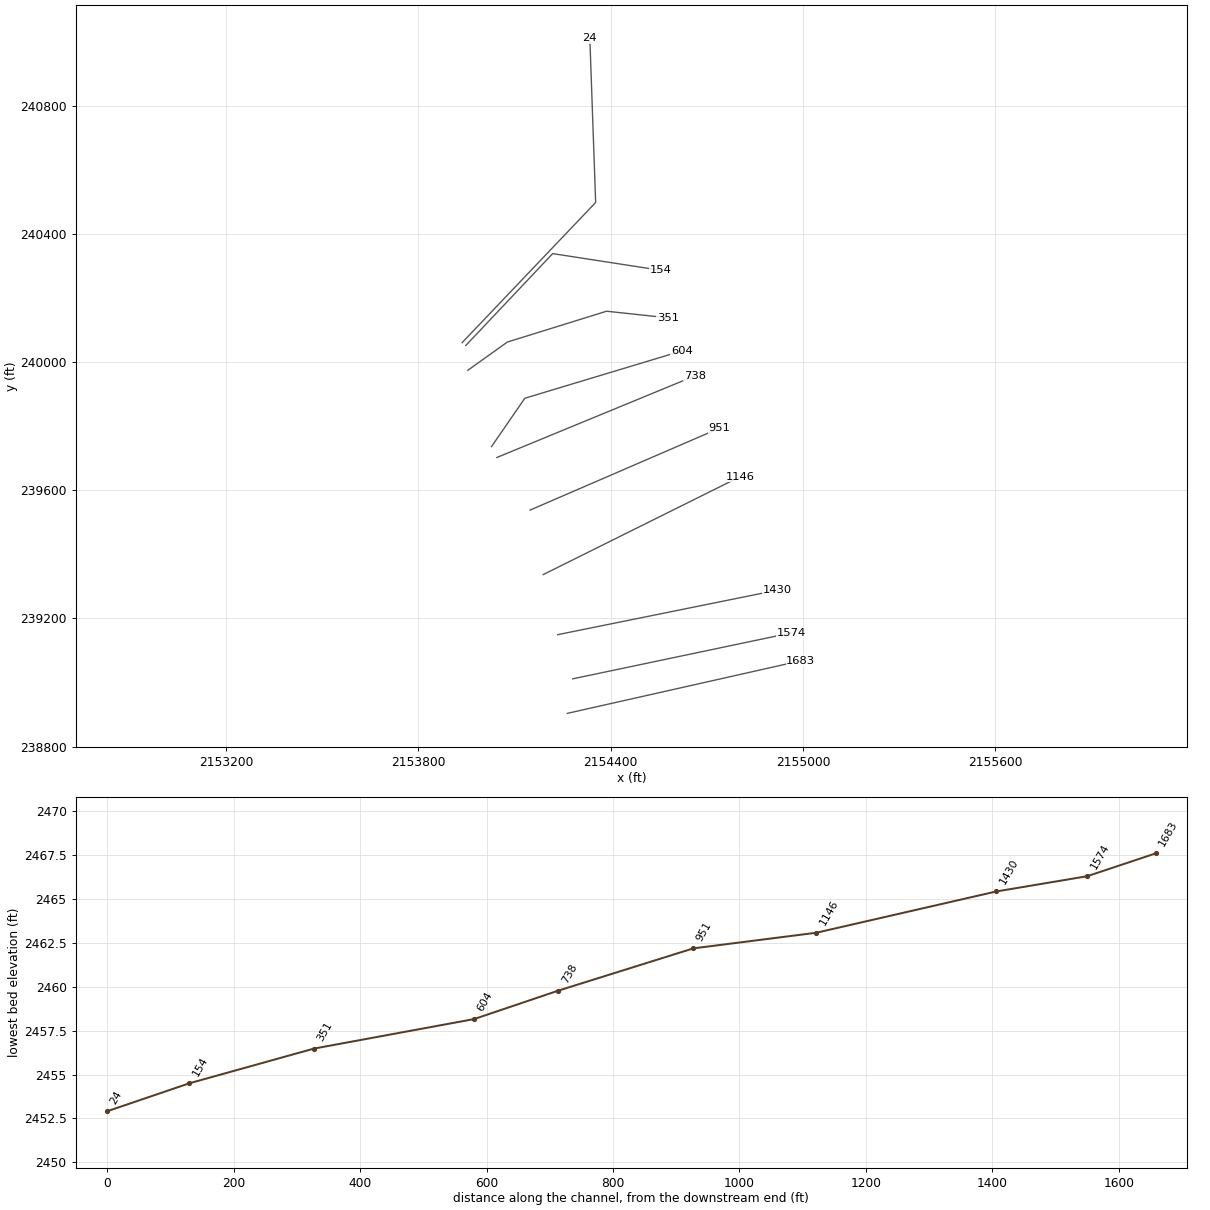
HEC-RAS study LLAURELCK.prj: LLAURELCK

--- LLAURELCK.g01 (geometry) --- (continued)

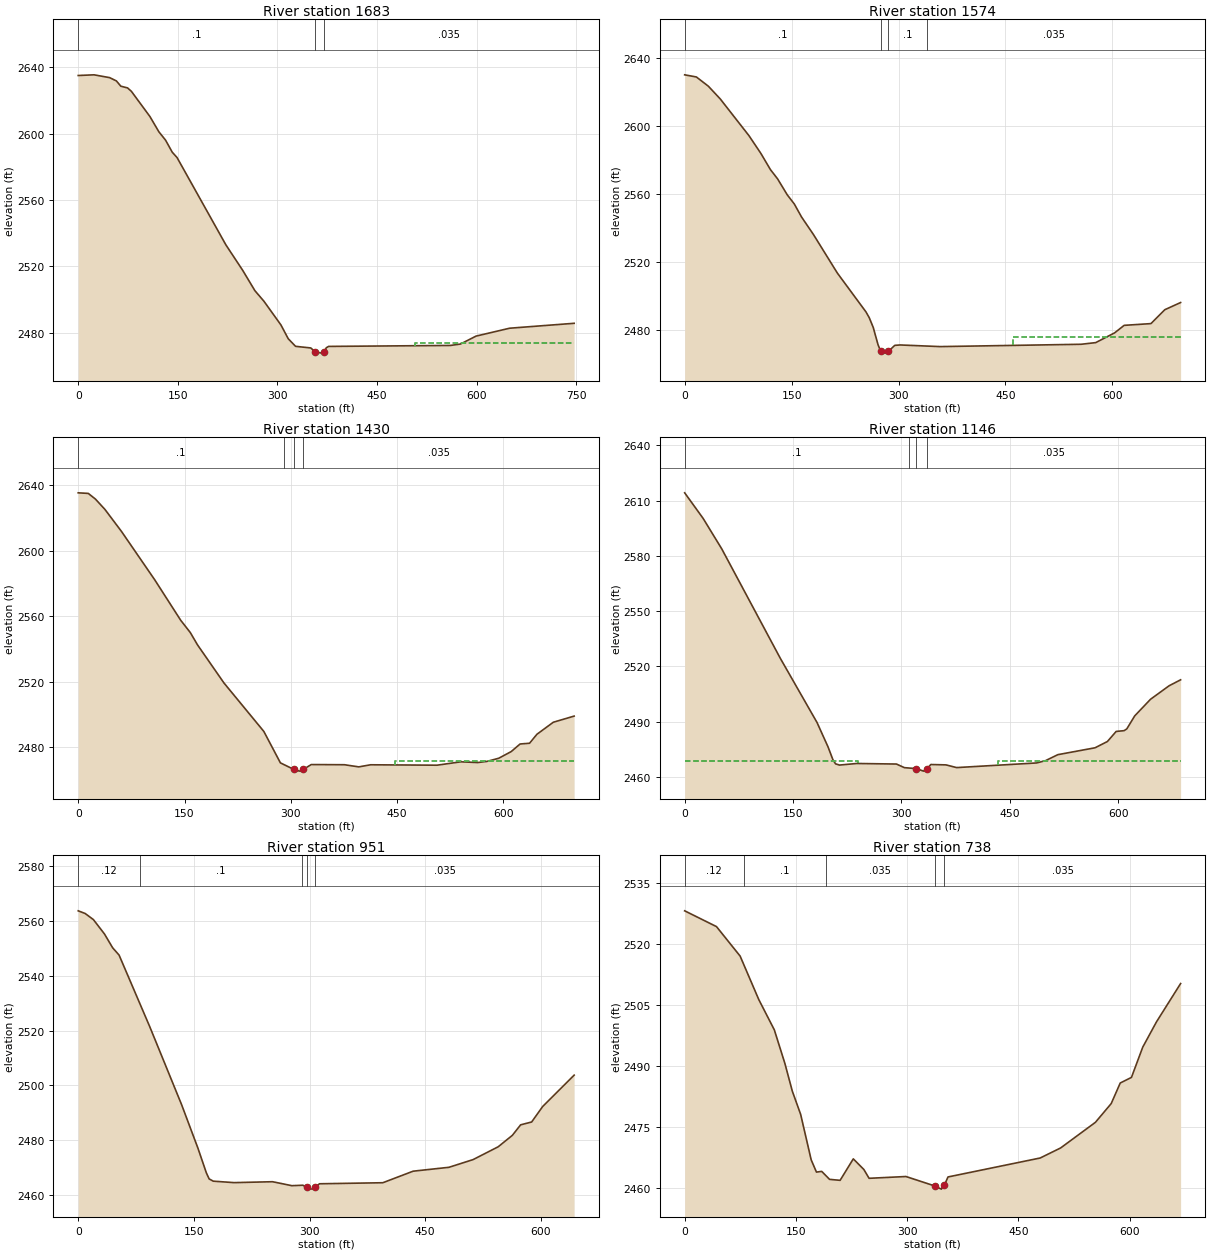
Type RM Length L Ch R = 1 ,1683    ,107.9,108.3,107.9
XS GIS Cut Line= 2
2154264.64784715238903.6634920782154992.97467171239067.671902944
#Sta/Elev= 30
       0 2635.03    23.9 2635.43    47.4 2633.73    57.5 2631.74    64.2 2628.56
    74.3 2627.54    80.1 2625.45     108 2610.26   121.4 2601.09   131.5 2596.04
   141.6 2588.75   148.8 2585.54   222.3  2532.9   247.6 2517.55     266 2505.26
   279.5 2498.94   305.2 2484.59   316.2 2476.27   327.2  2471.7   350.1 2470.72
   356.8 2468.37   366.9  2467.6   370.3 2468.52   373.6 2470.89     377 2471.65
   560.5 2472.23   575.4 2473.07   598.9 2477.86   649.4 2482.62   746.6 2485.59
#Mann= 3 ,-1 , 0
       0      .1       0   356.8    .045       0   370.3    .035       0
#XS Ineff= 2 , 0
                          506.53         2473.63
Permanent Ineff=
       F       F
Bank Sta=356.8,370.3
XS Rating Curve= 0 ,0
Exp/Cntr(USF)=0,0
Exp/Cntr=0.3,0.1

Type RM Length L Ch R = 1 ,1574    ,144,143.9,143.8
XS GIS Cut Line= 2
2154281.72974004239011.4894780862154962.58192578239154.567111321
#Sta/Elev= 30
       0 2630.03    16.4 2628.77    33.2 2623.34    49.9 2615.85    90.2 2594.23
   106.9 2583.79   120.3 2574.27   130.4 2568.79   143.8 2559.49   153.9 2553.97
   163.9 2546.42   180.7 2536.04   214.2 2513.39   254.4  2490.5   258.9 2487.15
   264.5 2481.43   271.2  2471.3   274.8 2467.59   277.9  2466.3   285.7 2467.27
   294.7 2470.87   302.3  2471.1   358.4 2470.14   556.2 2471.51   576.6 2472.48
   603.1 2478.22   616.5 2482.64   654.1 2483.67   673.5 2491.84   695.7 2496.07
#Mann= 4 ,-1 , 0
       0      .1       0   274.8    .045       0   285.7      .1       0
     340    .035       0
#XS Ineff= 2 , 0
                          460.53         2475.94
Permanent Ineff=
       F       F
Bank Sta=274.8,285.7
XS Rating Curve= 0 ,0
Exp/Cntr(USF)=0,0
Exp/Cntr=0.3,0.1

Type RM Length L Ch R = 1 ,1430    ,280.5,284.4,287
XS GIS Cut Line= 2
     2154234.666      239149.291      2154920.43       239288.18
#Sta/Elev= 30
       0 2635.29    14.2 2634.93    24.2 2631.51    37.6 2625.22    61.1  2611.7
   107.9 2582.24   144.7 2557.45   158.1 2550.04   168.3  2542.5   205.7  2519.2
   261.9 2489.65   285.3 2470.46   304.22466.478   312.1 2465.43   317.7 2466.52
   328.8 2469.44   375.7 2469.33   395.8 2468.02   412.5  2469.3   506.3 2469.05
   539.7 2471.11   563.6 2470.67   576.6 2471.35   593.3 2473.29   610.9 2477.36
   623.4 2481.99   636.8 2482.45   647.1 2487.89   670.3 2495.27   699.7 2499.02
#Mann= 4 ,-1 , 0
       0      .1       0     290    .035       0   304.2    .045       0
   317.7    .035       0
#XS Ineff= 2 , 0
                          447.63         2471.59
Permanent Ineff=
       F       F
Bank Sta=304.2,317.7
XS Rating Curve= 0 ,0
Exp/Cntr=0.3,0.1

Type RM Length L Ch R = 1 ,1146    ,194.7,194.5,193.5
XS GIS Cut Line= 2
     2154189.527      239336.791     2154804.111      239642.347
#Sta/Elev= 30
       0 2614.24    25.6 2600.31    51.3 2583.81   132.3  2524.4   183.2 2489.47
   198.4 2476.26   205.2 2469.25   208.8 2467.04   214.3 2466.37   238.1 2467.23
   293.1 2466.93   304.1 2464.97   320.72464.434   330.6 2463.08   335.32464.325
   340.7 2466.67   361.7 2466.47   376.4    2465   487.2 2467.52   499.4 2468.77
   516.5 2472.02     568 2475.76   585.1 2479.17   597.2 2484.64   608.2 2485.06
   611.9 2486.01   622.9  2493.1   644.8 2502.12   670.5 2509.45   686.4 2512.68
#Mann= 4 ,-1 , 0
       0      .1       0     310    .035       0   320.7    .045       0
   335.3    .035       0
#XS Ineff= 2 , 0
          239.36 2468.49  433.45         2468.57
Permanent Ineff=
       F       F
Bank Sta=320.7,335.3
XS Rating Curve= 0 ,0
Exp/Cntr=0.3,0.1

Type RM Length L Ch R = 1 ,951     ,211.9,213.8,211.4
XS GIS Cut Line= 2
2154148.49468541239538.0948916132154738.77268541239793.302891613
#Sta/Elev= 30
       0 2563.66       9 2562.69    19.7 2560.46      34 2555.24    44.7 2550.17
      53 2547.52    92.9 2521.33   134.1 2492.97   155.3 2477.08   166.2  2468.1
   169.8  2465.9   175.2 2465.09     202 2464.56     252 2464.89     277 2463.45
   291.3 2463.61  296.44 2462.85     302 2462.19   307.5 2462.85   312.8 2464.14
     395 2464.52   434.3 2468.73   480.8 2470.15   512.1 2472.96   544.6 2477.63
     563 2481.81   573.7 2485.63     588 2486.67   602.3 2492.32   643.1 2503.75
#Mann= 5 ,-1 , 0
       0     .12       0      80      .1       0     290    .035       0
  296.44    .045       0   307.5    .035       0
Bank Sta=296.44,307.5
XS Rating Curve= 0 ,0
Exp/Cntr=0.3,0.1

Type RM Length L Ch R = 1 ,738     ,133.5,133.2,131.1
XS GIS Cut Line= 2
2154044.91158848239702.2090868082154663.27009534239957.117513837
#Sta/Elev= 30
       0 2528.19    42.9 2524.31    74.8 2517.06    99.9 2506.39   120.9 2498.93
   135.1  2490.7   145.2 2483.84   156.4 2478.16   170.6 2466.98   177.7 2463.97
   184.8 2464.14   195.4 2462.18   209.6 2461.94   227.4 2467.22   241.6 2464.61
   248.7 2462.44   298.4 2462.88   337.4 2460.55   346.2 2459.78   350.3 2460.79
   355.1 2462.77   479.4 2467.43     507  2469.9   553.9  2476.2   575.2 2480.81
   587.4 2485.87   602.5 2487.24   617.7 2494.67   636.2 2500.88   668.8 2510.32
#Mann= 5 ,-1 , 0
       0     .12       0      80      .1       0     190    .035       0
   337.4    .045       0   350.3    .035       0
Bank Sta=337.4,350.3
XS Rating Curve= 0 ,0
Exp/Cntr(USF)=0,0
Exp/Cntr=0.3,0.1

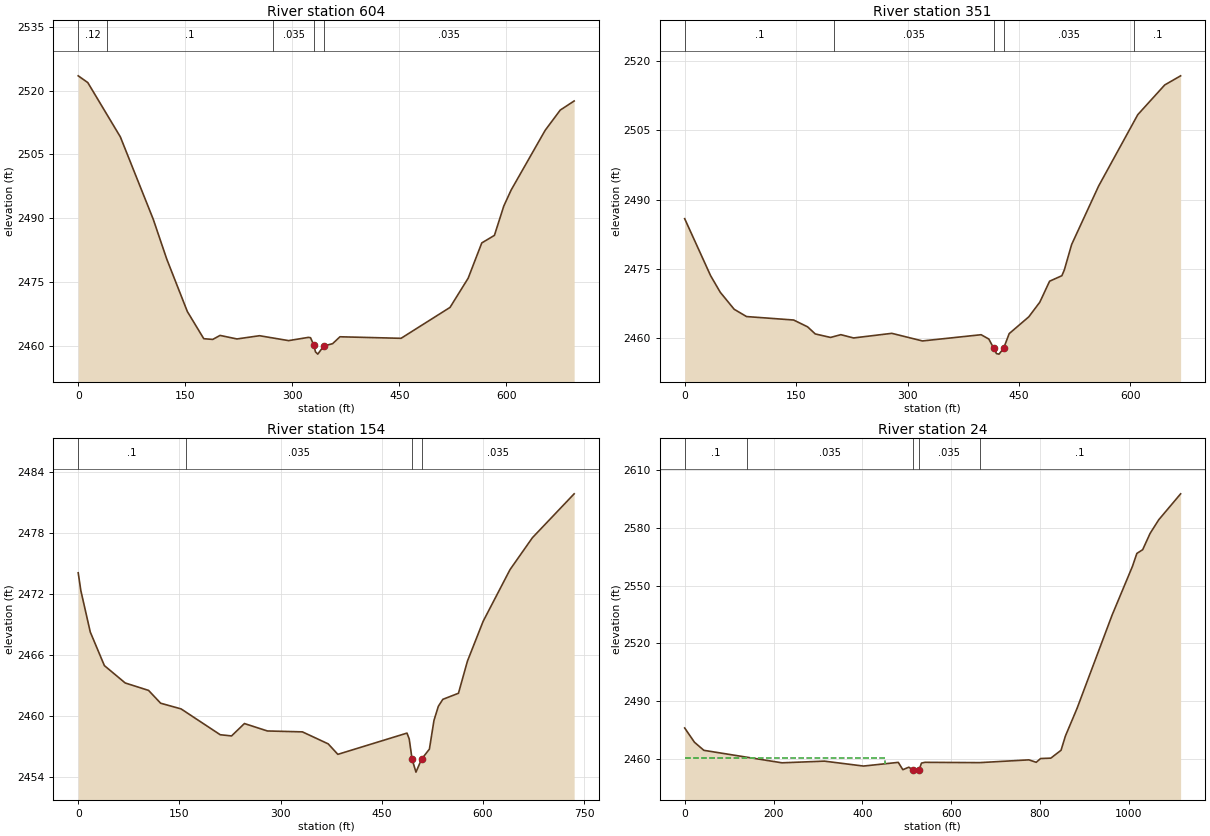
Type RM Length L Ch R = 1 ,604     ,252,253.1,250.2
XS GIS Cut Line= 3
     2154028.069      239736.097     2154132.236      239887.138
     2154621.819      240034.708
#Sta/Elev= 30
       0 2523.45    13.4 2521.87      59 2509.14   105.1 2489.81     124 2480.48
   152.9 2468.15   175.9 2461.78   188.5 2461.61   198.7 2462.55   222.4 2461.72
     254 2462.48   294.7 2461.33   322.5 2462.09   325.5 2462.01   330.12460.257
   332.4  2458.7   335.6 2458.16   344.12460.068   356.4 2460.61   366.7 2462.23
   452.3 2461.87   520.9 2469.12   546.3 2475.97   565.4 2484.25   583.1 2486.02
   596.2 2492.89   606.5 2496.65   654.2 2510.67   675.3 2515.41   694.8 2517.55
#Mann= 5 ,-1 , 0
       0     .12       0      40      .1       0  273.48    .035       0
   330.1    .045       0   344.1    .035       0
Bank Sta=330.1,344.1
XS Rating Curve= 0 ,0
Exp/Cntr=0.3,0.1

Type RM Length L Ch R = 1 ,351     ,197.4,197.4,197.4
XS GIS Cut Line= 4
2153954.40933036239974.4789158982154077.67333036240062.496609591
2154387.16051051240158.7146696422154578.25191892240138.273957949
#Sta/Elev= 30
       0 2485.86    34.9  2473.5    47.9  2469.9    66.7  2466.2    83.3 2464.63
   146.7 2463.88   165.5  2462.4   175.8 2460.86   196.4  2460.1   210.2  2460.7
   227.4 2459.99   278.9 2460.99   320.1 2459.34   399.1 2460.69   409.5 2459.75
   415.82457.844   419.8 2456.59   423.2 2456.48   429.32457.701   436.9 2460.93
   463.3 2464.57   478.1 2467.74   491.3  2472.3   507.8 2473.49   511.1 2474.73
     521 2480.27   557.3 2492.94     610 2508.42   646.3 2514.87   667.7 2516.85
#Mann= 5 ,-1 , 0
       0      .1       0  201.46    .035       0   415.8    .045       0
   429.3    .035       0  605.56      .1       0
Bank Sta=415.8,429.3
XS Rating Curve= 0 ,0
Exp/Cntr=0.3,0.1

Type RM Length L Ch R = 1 ,154     ,129.7,129.7,129.7
XS GIS Cut Line= 3
2153948.06537241240051.916528514     2154219.041      240338.527
     2154555.847      240286.444
#Sta/Elev= 30
       0 2474.11     3.9 2472.36    17.9 2468.28    38.8 2464.98    69.7 2463.27
   104.3 2462.54   122.2 2461.28   152.5 2460.72   210.5 2458.18   227.3 2458.06
   246.4 2459.28   280.4 2458.55   332.4 2458.46   370.6 2457.28   384.9 2456.25
   487.4 2458.34   490.7 2457.76     4952455.757   500.7  2454.5   509.12455.787
   520.6 2456.76   527.4 2459.59   533.9 2460.98   540.5 2461.66   563.7 2462.26
     577 2465.42   600.3 2469.34   640.1 2474.42   673.3 2477.56   735.2 2481.88
#Mann= 4 ,-1 , 0
       0      .1       0     160    .035       0     495    .045       0
   509.1    .035       0
Bank Sta=495,509.1
XS Rating Curve= 0 ,0
Exp/Cntr=0.3,0.1

Type RM Length L Ch R = 1 ,24      ,,,
XS GIS Cut Line= 3
2153936.61189032240060.7899521512154353.17638856240498.053307453
2154335.06488864241010.350019582
#Sta/Elev= 30
       0  2475.9      22 2468.48    43.2 2464.26     1402460.671   219.2 2457.76
   314.5 2458.63   402.6 2456.07   480.8 2457.99   491.2 2454.18   504.6 2455.47
   513.8 2454.12   520.9 2452.91   527.9 2454.21   533.1 2457.62     541 2458.01
  663.922457.856   774.9  2459.3   791.4 2458.03   801.3 2459.99   824.3 2460.19
   847.3 2464.29   857.1  2471.7   883.4 2486.14   962.2 2534.66  1008.1 2560.09
    1018  2566.8  1031.1 2568.75  1047.8 2577.22  1067.2  2584.3  1116.5 2597.83
#Mann= 5 ,-1 , 0
       0      .1       0     140    .035       0   513.8    .045       0
   527.9    .035       0  663.92      .1       0
#XS Ineff= 2 , 0
          450.71 2460.38
Permanent Ineff=
       F       F
Bank Sta=513.8,527.9
XS Rating Curve= 0 ,0
Exp/Cntr=0.3,0.1
LCMann Table=0

Chan Stop Cuts=-1
Use User Specified Reach Order=0
Composite Channel Slope=5